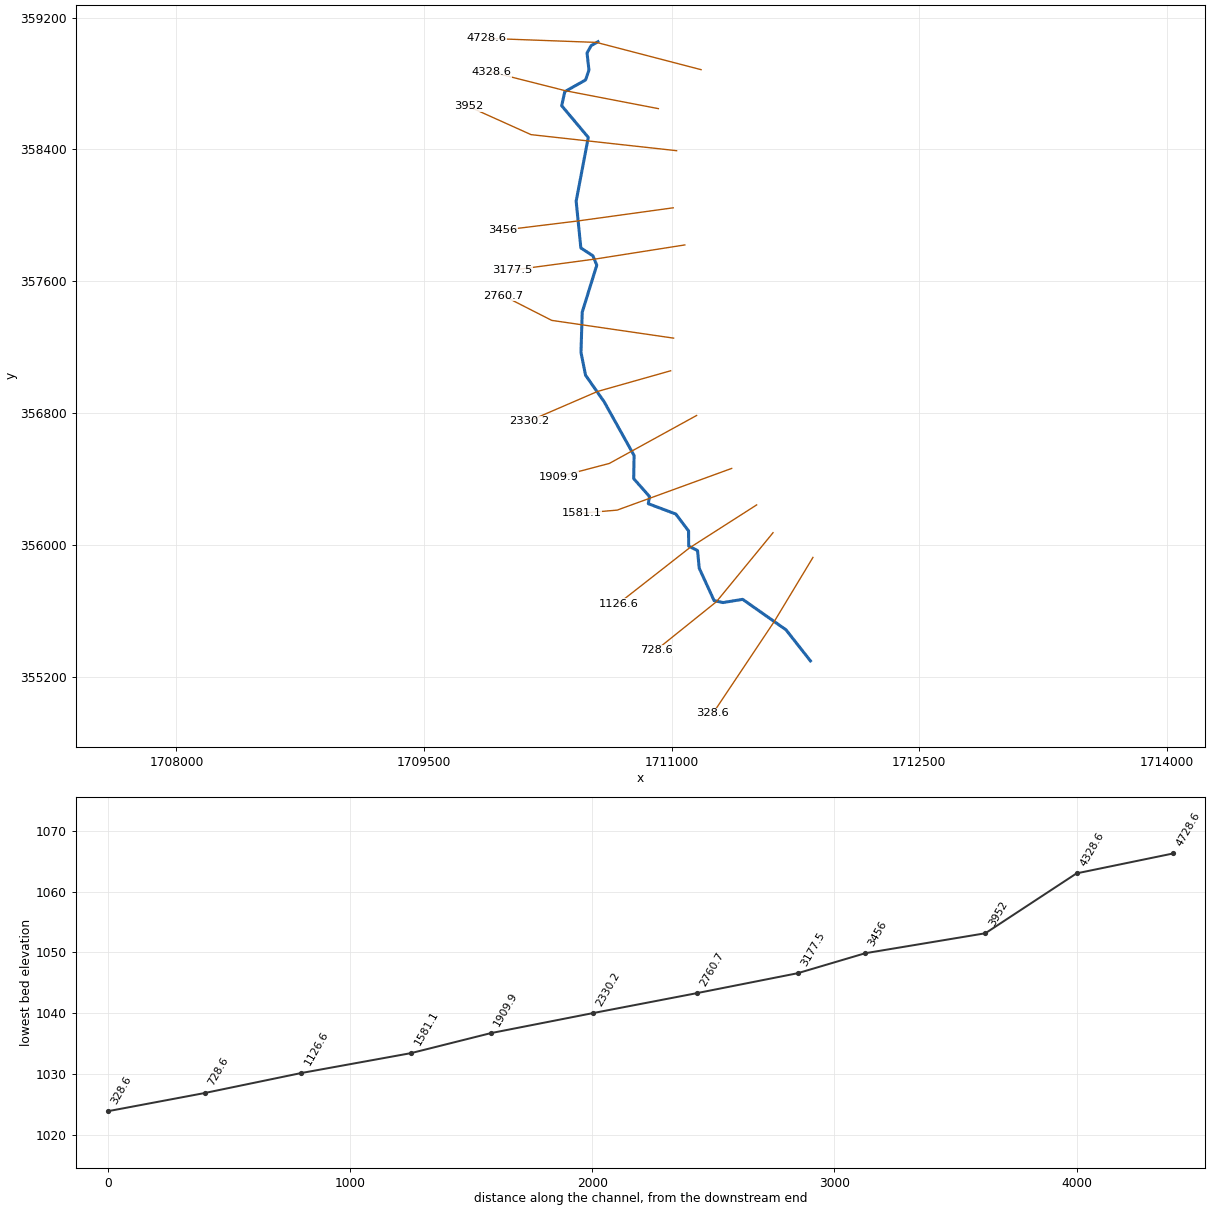
--- RdFrk.prj (project) ---

Proj Title=RdFrk
Current Plan=p01
Geom File=g01
Flow File=f01
Plan File=p01
DSS Export Rating Curves=0
DSS Export Rating Curve Sorted=0
DSS Export Volume Flow Curves=0
DXF OffsetX=0
DXF OffsetY=0
DXF ScaleX=0
DXF ScaleY=0

--- RdFrk.p01 (plan) ---

Plan Title=Floodplain
Program Version=4.00
Geom File=g01
Flow File=f01
K Sum by GR=0
Std Step Tol=0.01
Critical Tol=0.01
Num of Std Step Trials=20
Max Error Tol=0.3
Flow Tol Ratio=0.001
Split Flow NTrial=30
Split Flow Tol=0.02
Split Flow Ratio=0.02
Log Output Level=0
Friction Slope Method=1
Unsteady Friction Slope Method=2
Unsteady Bridges Friction Slope Method=1
Global Log Level=0
CheckData=False
Run HTab=0
Run UNet=0
Run PostProcess=0
UNET Theta=0
UNET Theta Warmup=0
UNET ZTol=0
UNET ZSATol=0
UNET MxIter=0
UNET MaxInSteps=0
UNET DtIC=0
UNET DtMin=0
UNET MaxCRTS=0
UNET WFStab=0
UNET SFStab=0
UNET WFX=0
UNET SFX=0
UNET DSS MLevel=0
UNET DZMax Abort=0
UNET Convert EG Bridges=0
UNET Use Existing IB Tables=0
UNET Froude Limit=0
UNET Froude Power=0
Write IC File=0
Echo Input=False
Echo Output=False
Write Detailed=0

--- RdFrk.f01 (steady flow) ---

Flow Title=NFF Regression Equation
Program Version=4.00
Number of Profiles=1
Profile Names=P100yr
River Rch & RM=RdFrk,Main      ,4728.6
538.2984
River Rch & RM=RdFrk,Main      ,4328.6
709.0545
River Rch & RM=RdFrk,Main      ,3456
751.6076
River Rch & RM=RdFrk,Main      ,2330.2
804.5830
River Rch & RM=RdFrk,Main      ,328.6
866.6811
Boundary for River Rch & Prof#=RdFrk,Main      ,1
Up Type=0
Dn Type=3
Dn Slope=0.007952

--- RdFrk.g01 (geometry) ---

Geom Title=USGS 3m DEM
Program Version=4.00

River Reach=RdFrk     ,Main
Reach XY= 30
     1710553.843      359053.377     1710512.672      359029.738
     1710487.566      358985.234     1710499.188      358881.126
     1710478.610      358821.251     1710352.821      358750.110
     1710334.066      358664.753     1710495.079      358472.660
     1710421.670      358085.172     1710450.155      357801.369
     1710522.785      357754.161     1710546.719      357697.252
     1710458.397      357411.584     1710450.897      357167.472
     1710478.590      357028.944     1710592.026      356866.463
     1710772.524      356541.486     1710770.246      356401.126
     1710866.108      356292.499     1710858.616      356249.099
     1711025.220      356186.222     1711102.736      356083.583
     1711103.079      355991.497     1711156.992      355964.571
     1711167.121      355857.487     1711257.359      355660.561
     1711311.286      355648.901     1711430.316      355668.394
     1711692.989      355483.339     1711840.911      355294.685

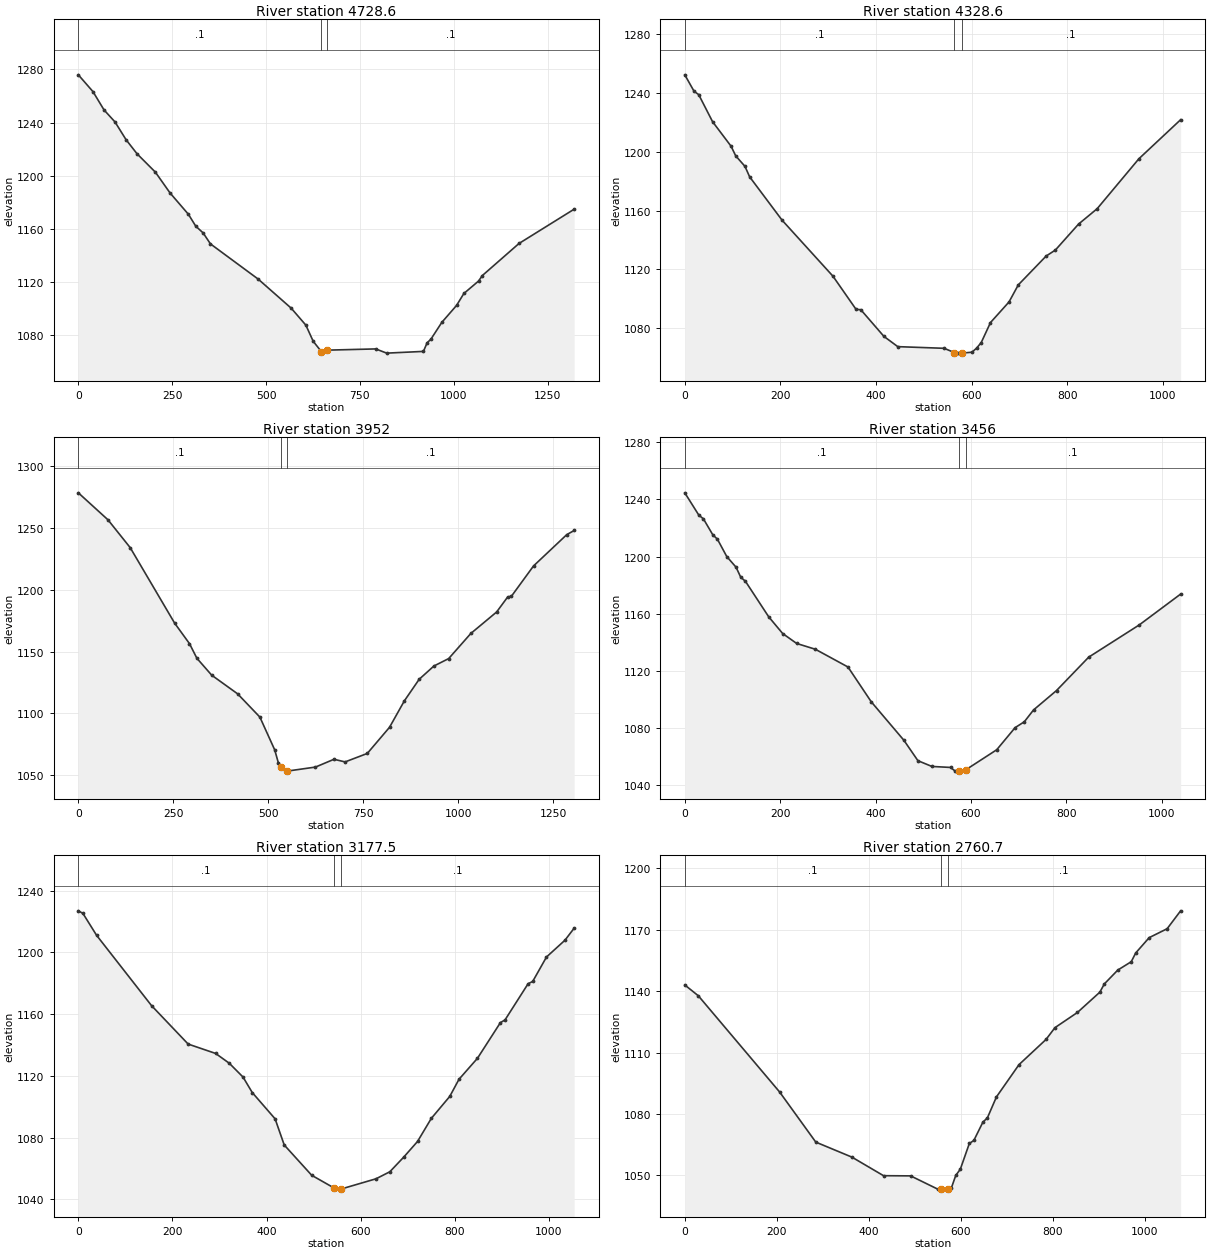
Type RM Length L Ch R = 1 ,4728.6,403.833,400,383.932
XS GIS Cut Line= 3
     1711178.617      358883.649     1710544.788      359049.133
     1709879.441      359073.885
#Sta/Elev= 30
       0 1275.92    39.1 1263.23    68.4 1249.50    97.8 1240.39   127.1 1227.07
   156.4 1216.44   205.3 1202.59   244.4 1186.90   293.3 1170.84   312.9 1161.87
   332.4 1156.85   352.0 1148.55   479.1 1122.04   567.1 1100.13   606.2 1087.33
   625.7 1075.20   647.6 1067.37   662.6 1068.51   792.2 1069.44   821.5 1066.27
   919.4 1067.57   929.2 1074.08   939.0 1076.66   968.4 1089.46  1007.6 1102.19
  1027.1 1111.20  1066.3 1120.59  1076.1 1124.66  1174.0 1148.88  1320.9 1174.71
#Mann= 3 , 0 , 0
       0     0.1       0   647.6   0.045       0   662.6     0.1       0
Bank Sta=   647.6,   662.6
Exp/Cntr=0.3,0.1

Type RM Length L Ch R = 1 ,4328.6,376.39,376.602,379.213
XS GIS Cut Line= 3
     1710919.779      358647.169     1710358.661      358755.425
     1709907.281      358869.729
#Sta/Elev= 30
       0 1252.40    19.4 1241.19    29.1 1238.92    58.1 1220.49    96.9 1203.76
   106.5 1197.25   125.9 1190.09   135.6 1182.98   203.4 1153.50   309.9 1115.35
   358.4 1092.70   368.1 1092.56   416.5 1074.38   445.5 1067.40   542.4 1066.27
     564 1063.37   571.5 1062.99     579 1062.99   600.6 1063.61   610.3 1066.38
   620.0 1070.16   639.4 1083.80   678.2 1097.84   697.6 1109.45   755.8 1129.06
   775.2 1133.16   823.7 1150.84   862.5 1161.28   949.8 1195.27  1037.1 1221.85
#Mann= 3 , 0 , 0
       0     0.1       0     564   0.045       0     579     0.1       0
Bank Sta=     564,     579
Exp/Cntr=0.3,0.1

Type RM Length L Ch R = 1 ,3952,490.407,496.025,501.38
XS GIS Cut Line= 3
     1711030.140      358391.818     1710148.556      358489.256
     1709768.083      358660.933
#Sta/Elev= 30
       0 1278.63    78.0 1256.76   136.5 1234.20   253.4 1173.03   292.4 1156.45
   311.9 1144.59   350.9 1130.88   419.1 1115.76   477.6 1096.93   516.6 1070.38
   526.3 1059.79   533.9 1056.87   545.8 1053.15   548.9 1053.15   623.8 1056.43
   672.5 1062.74   701.8 1060.62   760.2 1067.48   818.7 1088.67   857.7 1110.08
   896.7 1127.57   935.5 1138.32   974.3 1144.33  1032.6 1164.69  1100.5 1182.10
  1129.6 1194.29  1139.3 1194.81  1197.6 1219.41  1284.9 1244.74  1304.4 1248.11
#Mann= 3 , 0 , 0
       0     0.1       0   533.9   0.045       0   548.9     0.1       0
Bank Sta=   533.9,   548.9
Exp/Cntr=0.3,0.1

Type RM Length L Ch R = 1 ,3456,277.762,278.455,278.773
XS GIS Cut Line= 3
     1711009.732      358045.181     1710428.838      357964.863
     1709979.225      357909.612
#Sta/Elev= 30
       0 1244.65    29.3 1229.09    39.1 1226.40    58.6 1215.33    68.4 1212.19
    88.0 1200.04   107.5 1192.58   117.3 1185.56   127.1 1182.75   175.9 1157.87
   205.2 1146.16   234.6 1139.21   273.7 1135.17   342.1 1122.74   390.9 1098.38
   459.4 1071.42   488.7 1057.17   518.0 1053.15   557.1 1052.45   566.9 1049.87
   573.9 1049.87   588.9 1050.76   653.9 1064.83   692.4 1080.30   711.7 1084.40
   731.0 1092.67   779.2 1106.26   846.7 1129.64   952.7 1152.20  1039.4 1173.78
#Mann= 3 , 0 , 0
       0     0.1       0   573.9   0.045       0   588.9     0.1       0
Bank Sta=   573.9,   588.9
Exp/Cntr=0.3,0.1

Type RM Length L Ch R = 1 ,3177.5,423.603,416.83,410.697
XS GIS Cut Line= 3
     1711079.874      357819.804     1710541.923      357734.826
     1710037.300      357667.034
#Sta/Elev= 30
       0 1226.88     9.7 1225.24    38.9 1210.98   155.6 1165.46   233.4 1140.56
   291.8 1134.49   320.9 1128.12   350.1 1119.16   369.6 1109.18   418.2 1092.13
   437.6 1075.19   496.0 1055.56   542.7 1047.47   554.4 1046.59   557.7 1046.59
   632.7 1053.29   662.1 1057.85   691.5 1067.30   720.9 1077.46   750.2 1092.42
   789.4 1106.64   809.0 1117.74   848.2 1131.32   897.1 1154.47   906.9 1156.22
   955.9 1179.65   965.7 1181.13   995.0 1196.97  1034.2 1207.83  1053.8 1215.64
#Mann= 3 , 0 , 0
       0     0.1       0   542.7   0.045       0   557.7     0.1       0
Bank Sta=   542.7,   557.7
Exp/Cntr=0.3,0.1

Type RM Length L Ch R = 1 ,2760.7,420.422,430.526,442.909
XS GIS Cut Line= 3
     1711012.015      357254.025     1710273.834      357361.758
     1709978.474      357512.410
#Sta/Elev= 30
       0 1143.02    29.4 1137.73   206.1 1090.74   284.7 1066.27   363.2 1058.94
   431.9 1049.87   490.8 1049.78   549.7 1043.31   556.6 1043.31   571.6 1043.40
   579.1 1043.71   588.9 1050.01   598.8 1053.03   618.4 1065.60   628.2 1067.08
   647.8 1075.99   657.7 1078.14   677.3 1088.34   726.4 1104.12   785.0 1116.39
   804.5 1122.17   853.3 1129.58   902.0 1139.49   911.8 1143.52   941.0 1150.28
   970.3 1154.37   980.0 1158.65  1009.3 1166.13  1048.3 1170.48  1077.6 1179.22
#Mann= 3 , 0 , 0
       0     0.1       0   556.6   0.045       0   571.6     0.1       0
Bank Sta=   556.6,   571.6
Exp/Cntr=0.3,0.1

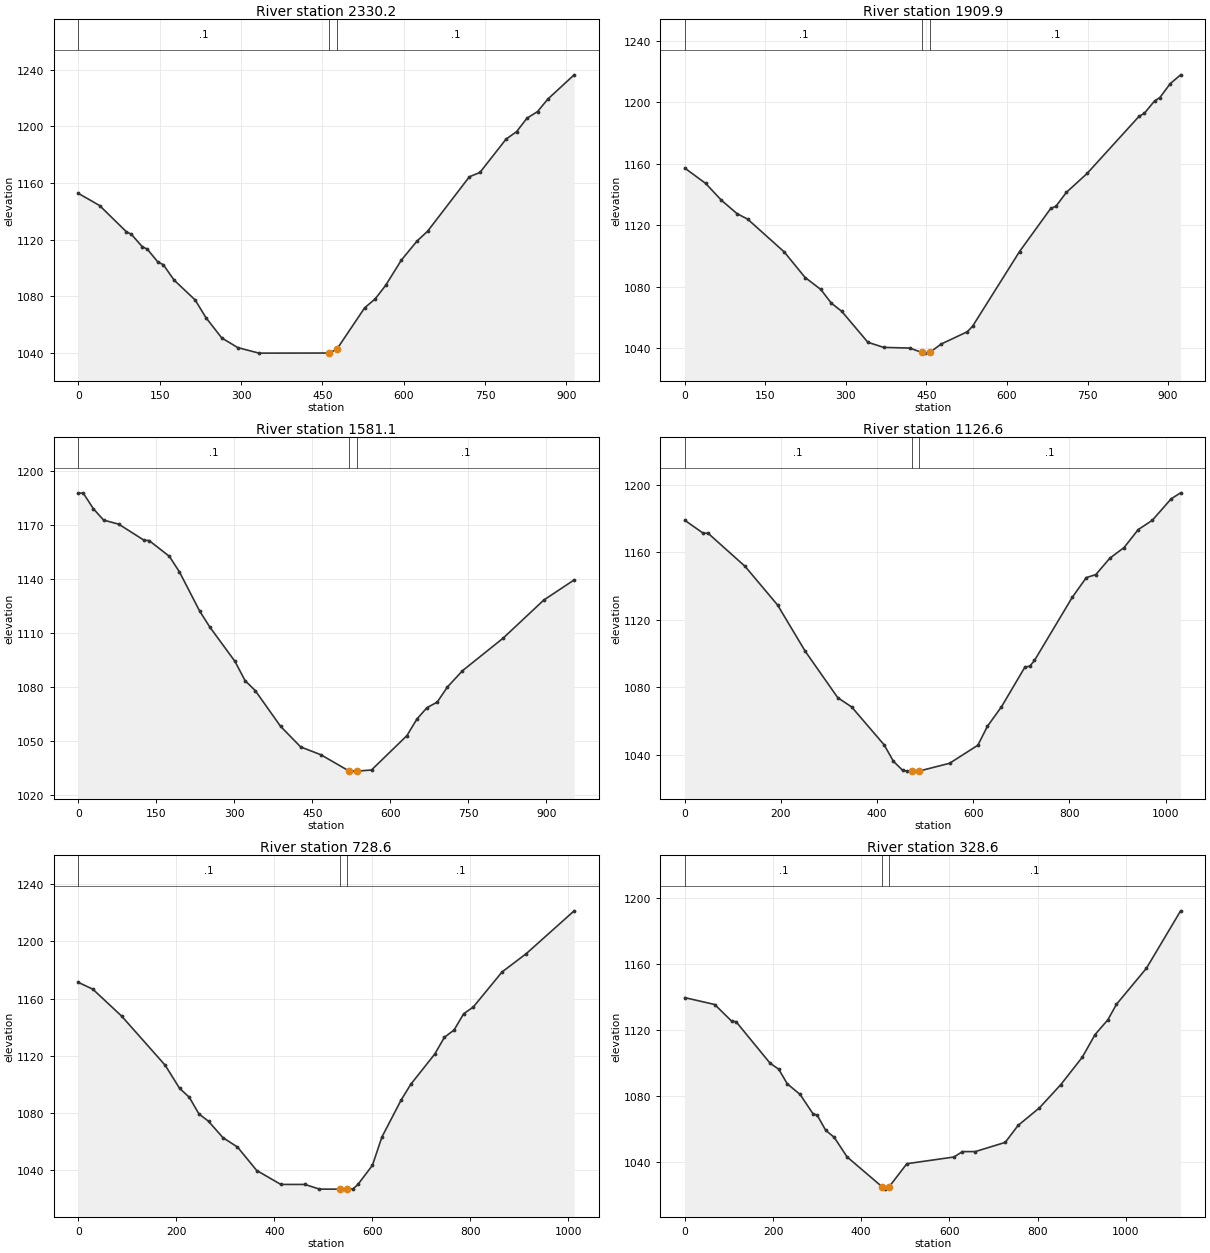
Type RM Length L Ch R = 1 ,2330.2,415.764,420.29,422.537
XS GIS Cut Line= 3
     1710994.169      357055.856     1710551.029      356930.231
     1710134.457      356749.997
#Sta/Elev= 30
       0 1152.76    39.2 1144.16    88.2 1125.81    98.0 1123.78   117.6 1115.25
   127.4 1113.29   147.0 1104.21   156.8 1102.41   176.4 1091.65   215.6 1077.48
   235.2 1065.13   264.6 1050.71   294.0 1043.94   333.2 1040.02   461.7 1040.09
   476.7 1042.71   528.2 1072.03   547.5 1078.27   566.8 1087.83   595.8 1105.66
   624.8 1119.16   644.1 1125.98   721.3 1164.47   740.7 1167.50   788.9 1191.02
   808.3 1196.29   827.6 1205.83   846.9 1210.45   866.2 1219.37   914.5 1236.39
#Mann= 3 , 0 , 0
       0     0.1       0   461.7   0.045       0   476.7     0.1       0
Bank Sta=   461.7,   476.7
Exp/Cntr=0.3,0.1

Type RM Length L Ch R = 1 ,1909.9,332.382,328.775,330.095
XS GIS Cut Line= 3
     1711151.472      356784.619     1710622.282      356493.255
     1710313.537      356411.871
#Sta/Elev= 30
       0 1157.16    39.0 1147.13    68.2 1136.22    97.4 1127.47   116.9 1123.97
   185.1 1102.62   224.1 1085.95   253.3 1078.17   272.8 1069.30   292.3 1063.93
   341.0 1043.80   370.3 1040.48   419.0 1040.02   441.8 1037.16   448.2 1036.74
   456.8 1037.33   477.4 1042.63   526.1 1050.65   535.9 1054.21   623.4 1102.84
   681.5 1130.89   691.2 1132.30   710.5 1141.30   749.2 1153.64   846.0 1190.83
   855.7 1192.73   875.0 1200.90   884.7 1203.02   904.0 1212.06   923.4 1217.83
#Mann= 3 , 0 , 0
       0     0.1       0   441.8   0.045       0   456.8     0.1       0
Bank Sta=   441.8,   456.8
Exp/Cntr=0.3,0.1

Type RM Length L Ch R = 1 ,1581.1,444.149,454.447,454.687
XS GIS Cut Line= 3
     1711363.834      356463.145     1710670.111      356210.045
     1710456.095      356191.775
#Sta/Elev= 30
       0 1187.67     9.7 1187.40    29.1 1178.79    48.6 1172.57    77.7 1170.29
   126.3 1161.42   136.0 1161.23   174.9 1152.52   194.3 1143.91   233.2 1122.18
   252.6 1113.37   301.2 1094.23   320.6 1083.58   340.1 1078.10   388.7 1058.31
   427.5 1046.85   466.4 1042.53   520.7 1033.48   524.7 1033.46   535.7 1033.46
   563.6 1034.09   631.6 1053.11   651.0 1062.36   670.4 1068.66   689.9 1071.67
   709.3 1080.00   738.5 1089.09   816.6 1107.13   894.7 1128.23   953.2 1139.42
#Mann= 3 , 0 , 0
       0     0.1       0   520.7   0.045       0   535.7     0.1       0
Bank Sta=   520.7,   535.7
Exp/Cntr=0.3,0.1

Type RM Length L Ch R = 1 ,1126.6,386.075,398.048,398.61
XS GIS Cut Line= 3
     1711515.133      356241.705     1711109.270      355981.404
     1710677.202      355642.457
#Sta/Elev= 30
       0 1179.00    38.6 1171.28    48.2 1171.38   125.4 1151.67   192.9 1128.77
   250.7 1101.21   318.2 1073.74   347.2 1068.23   414.7 1045.74   433.9 1036.04
   453.2 1030.62   462.9 1030.18   471.8 1030.18   486.8 1030.18   550.8 1034.84
   609.6 1045.57   629.3 1056.72   658.7 1068.36   707.7 1092.04   717.5 1092.41
   727.3 1095.83   805.8 1133.26   835.2 1145.02   854.8 1146.76   884.2 1156.56
   913.6 1162.82   943.1 1173.48   972.5 1179.03  1011.7 1191.77  1031.3 1195.30
#Mann= 3 , 0 , 0
       0     0.1       0   471.8   0.045       0   486.8     0.1       0
Bank Sta=   471.8,   486.8
Exp/Cntr=0.3,0.1

Type RM Length L Ch R = 1 ,728.6,396.857,400,407.087
XS GIS Cut Line= 3
     1711614.323      356072.887     1711271.561      355654.202
     1710905.007      355359.201
#Sta/Elev= 30
       0 1171.29    29.5 1166.57    88.5 1147.71   177.1 1113.47   206.6 1097.29
   226.3 1091.11   246.0 1079.47   265.6 1074.29   295.1 1062.84   324.7 1056.31
   364.0 1039.91   413.2 1030.18   462.4 1030.17   491.9 1026.90   533.6 1026.90
   548.6 1026.90   560.7 1027.12   570.5 1030.21   599.9 1043.47   619.5 1063.41
   658.7 1089.20   678.3 1100.15   727.3 1121.28   746.9 1132.96   766.6 1138.04
   786.2 1149.40   805.8 1154.10   864.6 1178.62   913.6 1191.29  1011.6 1221.28
#Mann= 3 , 0 , 0
       0     0.1       0   533.6   0.045       0   548.6     0.1       0
Bank Sta=   533.6,   548.6
Exp/Cntr=0.3,0.1

Type RM Length L Ch R = 1 ,328.6,339.378,328.597,318.845
XS GIS Cut Line= 3
     1711856.073      355922.856     1711621.236      355533.098
     1711250.020      354976.200
#Sta/Elev= 30
       0 1139.62    67.8 1135.46   106.5 1125.33   116.2 1125.09   193.6 1099.93
   213.0 1096.36   232.4 1087.52   261.4 1081.15   290.5 1069.51   300.1 1068.64
   319.5 1059.44   338.9 1055.19   367.9 1043.40   447.5 1025.30   455.0 1023.91
   462.5 1025.05   503.5 1039.27   610.2 1043.31   629.6 1046.58   658.7 1046.59
   726.6 1052.15   755.7 1062.40   804.2 1073.03   852.7 1087.09   901.2 1103.57
   930.3 1117.30   959.4 1126.26   978.8 1135.58  1046.7 1157.34  1124.3 1192.06
#Mann= 3 , 0 , 0
       0     0.1       0   447.5   0.045       0   462.5     0.1       0
Bank Sta=   447.5,   462.5
Exp/Cntr=0.3,0.1